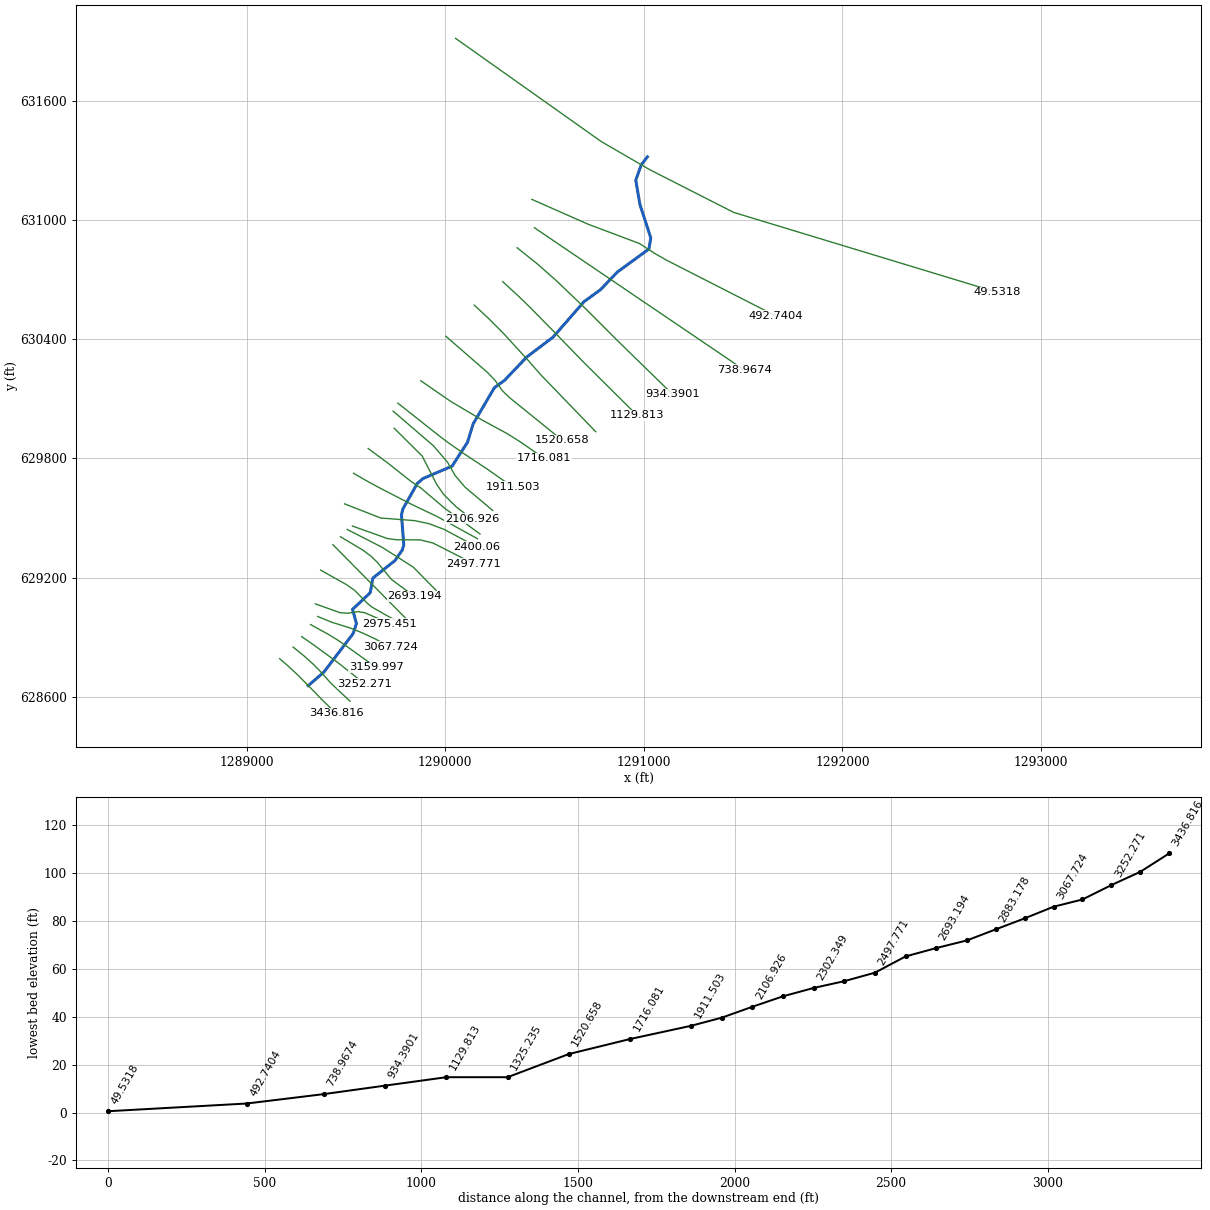
--- 782_ras.prj (project) ---

Proj Title=782
Current Plan=p01
Default Exp/Contr=0.3,0.1
English Units
Geom File=g01
Flow File=f01
Plan File=p01
Y Axis Title=Elevation
X Axis Title(PF)=Main Channel Distance
X Axis Title(XS)=Station
BEGIN DESCRIPTION:
RFD model 782 exported to HEC-RAS
END DESCRIPTION:

--- 782_ras.p01 (plan) ---

Plan Title=Plan 01
Program Version=4.10
Short Identifier=Plan 01
Geom File=g01
Flow File=f01
Subcritical Flow
Calc Critical at every XS
Secant Critical Depth

--- 782_ras.f01 (steady flow) ---

Flow Title=Flow 01
Program Version=5.01
Number of Profiles= 5
Profile Names=10yr,25yr,50yr,100yr,500yr
River Rch & RM=782,25,3436.816
  362.24  428.48  509.84  539.17  625.33
River Rch & RM=782,25,2790.905
  380.83  453.77  540.83  576.19  674.65
River Rch & RM=782,25,2595.483
  389.62   465.8  555.59  593.92  698.42
River Rch & RM=782,25,2497.771
  397.28  476.31   568.5  609.47  719.36
River Rch & RM=782,25, 2400.06
  528.89  661.17  796.66     891 1110.31
River Rch & RM=782,25,2302.349
  532.12  665.81   802.4  898.23 1120.62
River Rch & RM=782,25,2204.637
  534.26  668.87  806.21  903.02 1127.45
River Rch & RM=782,25,2009.215
  541.11  678.72  818.42  918.43 1149.47
River Rch & RM=782,25,1911.503
  555.95  700.09  844.95     952 1197.61
River Rch & RM=782,25,1716.081
   586.7  744.65  900.34 1022.52 1299.54
River Rch & RM=782,25,1520.658
  627.42  804.18  974.48 1117.77 1438.78
River Rch & RM=782,25,1325.235
  638.51  820.49  994.83 1144.07 1477.54
River Rch & RM=782,25,1129.813
  646.54  832.33  1009.6  1163.2 1505.81
River Rch & RM=782,25,934.3901
  730.94  958.01 1166.78 1368.92 1813.86
River Rch & RM=782,25,738.9674
   787.2 1042.99 1273.41  1510.5 2029.81
River Rch & RM=782,25,492.7404
  809.64 1077.14 1316.33 1567.92 2118.24
River Rch & RM=782,25, 49.5318
  814.13 1083.98 1324.94 1579.46 2136.07
Boundary for River Rch & Prof#=782,25,1
Up Type= 0
Dn Type= 2
Boundary for River Rch & Prof#=782,25,2
Up Type= 0
Dn Type= 2
Boundary for River Rch & Prof#=782,25,2
Up Type= 0
Dn Type= 2
Boundary for River Rch & Prof#=782,25,2
Up Type= 0
Dn Type= 2
Boundary for River Rch & Prof#=782,25,2
Up Type= 0
Dn Type= 2

--- 782_ras.g01 (geometry) ---

Geom Title=782
Program Version=4.10

River Reach=782,25
Reach XY= 30
1289309.54204214628656.3010351061289388.70868742628724.634345829
1289536.20864964628918.8009505271289552.87531281628969.634268299
1289532.87532082629040.4675811831289622.04196367629123.800887153
1289635.37529528629197.9675314281289746.20859846629285.467502147
1289783.70858899629339.634151638 1289791.2085875629364.634144008
1289779.54192868629515.4674329161289786.20859423629544.634090737
1289859.54190975629674.634049967 1289887.8752355629698.800708607
1290034.54186067629761.3006857341290112.04184139 629881.30064784
1290140.37516907629973.8006195281290247.04180959630155.467229158
1290298.70846215630192.9672165071290410.37509936630310.467178345
1290542.87506321630410.4671447131290698.70835581630588.800420523
1290781.20833319630648.8004003021290867.00573567630738.248408154
1291025.85990229 630854.133824841291034.97448564630910.123408154
1290980.28698561631078.0921581541290959.45365226631200.487991467
 1290987.4317506631278.3125107141291018.04740226631317.675491482

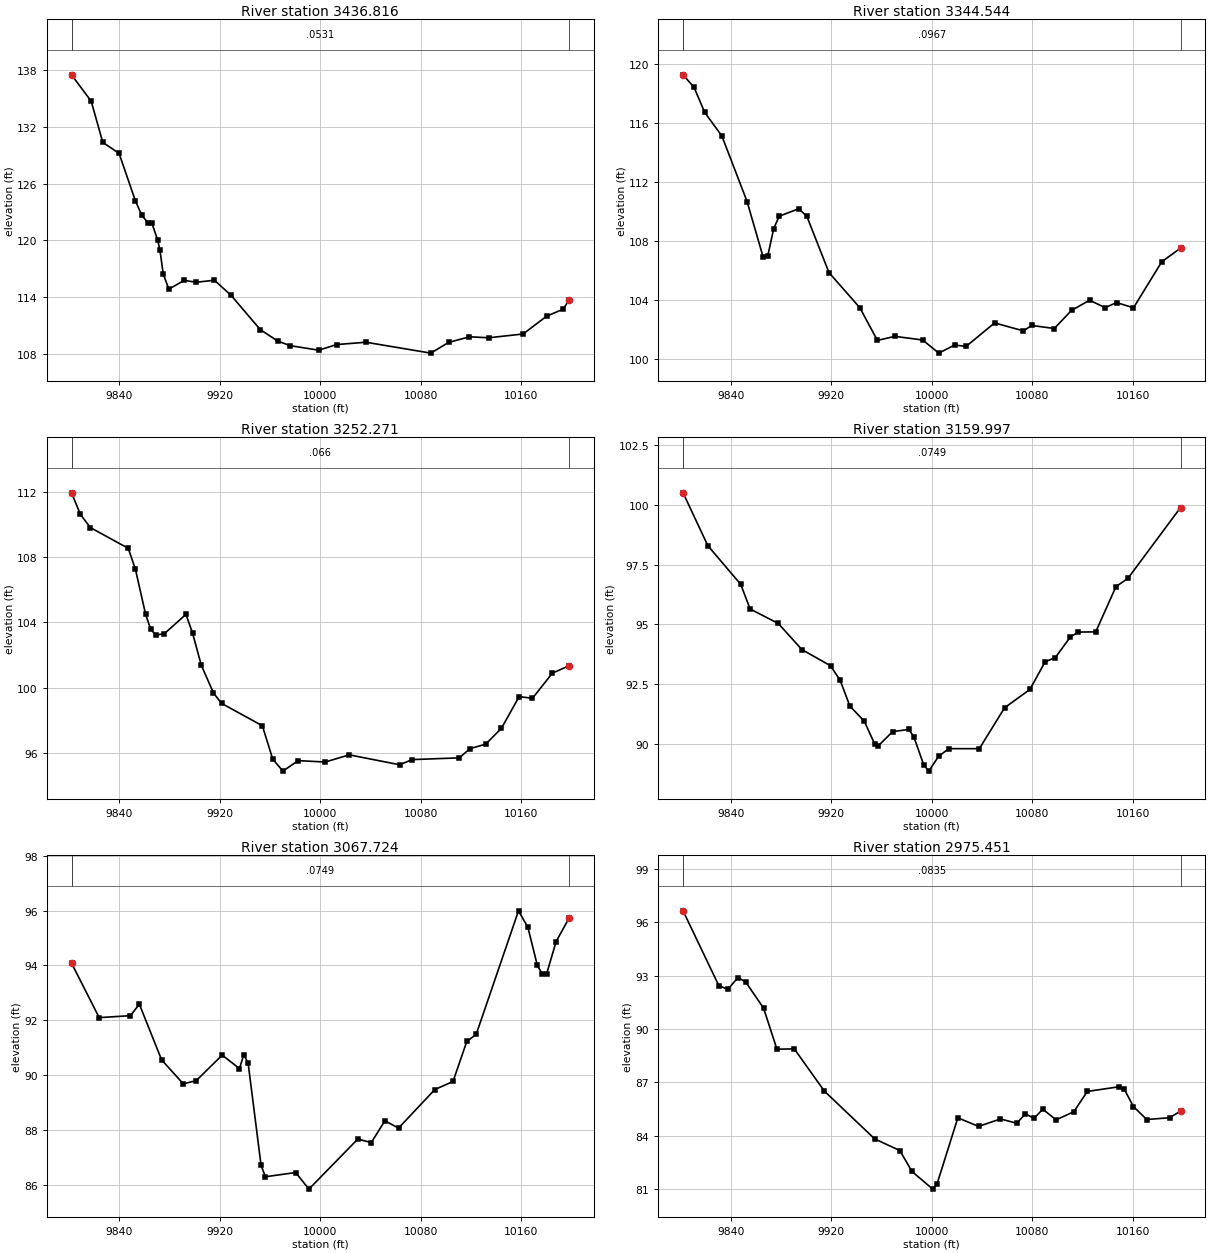
Type RM Length L Ch R = 1 ,3436.816,92.273000,92.273000,92.273000
XS GIS Cut Line= 6
1289165.83973619628792.4076562541289209.16898506628755.110888389
1289253.82338967628713.6569904541289309.56379673628657.715081335
1289384.22749231628581.0922697191289450.46389034628517.111234173
#Sta/Elev= 30
9801.928 137.507  9817.6134.71179826.802130.36949839.788129.20359852.775124.1829
9857.833122.67929862.707121.86429865.989121.79059870.465120.06829872.351118.9576
9874.942116.45449879.419114.8514 9891.64115.77489901.285115.57869915.751115.7928
9928.992114.19259952.233110.57059966.178109.3569 9976.13108.87299998.715108.3972
10013.02108.990910036.32109.238410088.03108.086410102.14109.215910118.77109.8126
10134.18  109.7110161.55110.111510180.16111.982810193.48112.738910198.08113.6841
#Mann= 3 , 0 , 0
9801.928  0.0531       09801.928  0.0531       010198.08  0.0531       0
#XS Ineff= 2 , 0
       09930.495        10120.57       0
Bank Sta=9801.928,10198.08
Exp/Cntr=0.3,0.1

Type RM Length L Ch R = 1 ,3344.544,92.273000,92.273000,92.273000
XS GIS Cut Line= 6
 1289233.6456641628850.8074642211289287.98078371628806.855266468
1289334.12314383628765.5732815881289365.58719942628734.154027979
1289424.40377146628668.6870021821289520.35628713628578.335948252
#Sta/Elev= 30
9801.945119.25719810.717118.40419819.156116.7108 9832.81115.11819852.915 110.667
9865.575106.93989869.327106.95419874.109108.83399878.511109.67389894.072110.1794
9900.522109.66149918.131105.8521 9942.74103.46419956.669101.25419970.598101.5274
9992.733 101.28210005.58100.391410018.16100.9395 10027.3100.846110049.97102.4384
10072.99101.899710079.49102.268210097.51102.060810111.28103.288510125.63103.9768
10138.07103.473910147.08103.8186 10160.6103.464710183.13106.588310198.06107.5066
#Mann= 3 , 0 , 0
9801.945  0.0967       09801.945  0.0967       010198.06  0.0967       0
#XS Ineff= 2 , 0
       09932.437        10101.39       0
Bank Sta=9801.945,10198.06
Exp/Cntr=0.3,0.1

Type RM Length L Ch R = 1 ,3252.271,92.273000,92.273000,92.273000
XS GIS Cut Line= 6
1289277.38015557628903.1461559441289344.21330433628856.586375499
1289437.58249712628788.3841448071289439.19996928 628787.20780141
1289463.74967888628769.1972147161289594.30385294628665.658143341
#Sta/Elev= 30
9801.922111.95059808.912110.63759816.909109.81719847.089108.54319852.828107.2486
9860.893104.49359864.891103.5911 9868.89103.22169875.787103.30119893.034104.4883
 9898.27 103.3479905.222101.37479914.95699.661549921.47499.021559953.89197.65093
9962.10395.611299970.22994.866389982.41795.5106210003.9595.4256310023.0895.86612
10063.3595.2548610073.0895.5737710110.77 95.681310119.14 96.2468 10131.796.52144
10144.2797.4958810158.3999.4436610168.9599.3333410184.79100.878410198.08101.3327
#Mann= 3 , 0 , 0
9801.922   0.066       09801.922   0.066       010198.08   0.066       0
#XS Ineff= 2 , 0
       09950.685        10071.95       0
Bank Sta=9801.922,10198.08
Exp/Cntr=0.3,0.1

Type RM Length L Ch R = 1 ,3159.997,92.273100,92.273100,92.273100
XS GIS Cut Line= 6
1289321.61976678628964.0865887311289410.59478216628915.198840044
1289454.14724178628888.7162731081289490.98123987628863.608208179
1289492.61970371628862.4612834911289653.05673972628748.010531139
#Sta/Elev= 30
9801.929100.49759821.63598.289589847.83996.671349855.32695.640789877.78795.03459
9896.50493.945819919.36493.266859927.04492.658019934.723 91.58529946.24290.94775
9954.42290.009679957.16789.908669968.817 90.51469981.69990.605139985.66990.29983
 9993.6189.119479997.58188.8626510005.6189.4935810013.6789.8023110037.8589.80103
   1005891.5138910078.1592.2784610090.2493.43525 10098.393.6043510110.3994.47484
10116.6494.6752410130.5494.6854610146.66 96.576210156.1896.9220810198.0899.88192
#Mann= 3 , 0 , 0
9801.929  0.0749       09801.929  0.0749       010198.08  0.0749       0
#XS Ineff= 2 , 0
       09944.128        10054.43       0
Bank Sta=9801.929,10198.08
Exp/Cntr=0.3,0.1

Type RM Length L Ch R = 1 ,3067.724,92.273000,92.273000,92.273000
XS GIS Cut Line= 6
 1289357.9035708629004.7402988641289425.93680804628976.563314975
1289523.83235418  628945.83183581289581.70452202628922.387574252
1289647.19928546628892.0859282321289721.90274872628851.041638796
#Sta/Elev= 30
9801.96394.081059823.99792.095289848.85592.167569855.95792.584819873.71290.55287
9890.96589.681849901.28189.800369921.91490.728899935.66890.237729939.10790.74392
9942.54690.443969952.86286.711099956.30186.294919980.41886.448829990.95985.84378
10029.8587.6678210040.6287.5411810051.4688.3353810062.3188.0686510091.2389.47477
10105.6989.7673610116.6691.2268210124.1591.4861110157.8495.9892110165.3395.38578
10172.8194.0018310176.5693.70421 10180.393.7022410187.7994.8700410198.0595.72083
#Mann= 3 , 0 , 0
9801.963  0.0749       09801.963  0.0749       010198.05  0.0749       0
#XS Ineff= 2 , 0
       09931.441        10033.81       0
Bank Sta=9801.963,10198.05
Exp/Cntr=0.3,0.1

Type RM Length L Ch R = 1 ,2975.451,92.273000,92.273000,92.273000
XS GIS Cut Line= 6
1289345.52560814629068.2700290641289470.98126618629023.464700535
1289509.82636388629021.1063945661289560.74433847629029.141586908
 1289593.6034421629023.9185029011289720.68793101628969.299936899
#Sta/Elev= 30
9802.00596.649159830.43592.442729837.563 92.22679845.68692.891739851.81892.65031
9866.07391.172039876.71988.860459890.52288.87992 9914.4786.502319954.51683.81155
9974.54283.157739984.16781.9817810000.7680.9853910004.0981.26276 10020.784.99972
10037.2284.51493 10054.684.9350910067.5984.69468 10074.585.22144 10081.484.97246
10088.3185.48497 10098.984.8835410113.0785.3443410123.7586.4838710149.2586.74875
10152.8986.6489310160.4485.63282 10171.184.9021310189.3285.0054110197.9685.37724
#Mann= 3 , 0 , 0
9802.005  0.0835       09802.005  0.0835       010197.96  0.0835       0
#XS Ineff= 2 , 0
       09964.273         10032.1       0
Bank Sta=9802.005,10197.96
Exp/Cntr=0.3,0.1

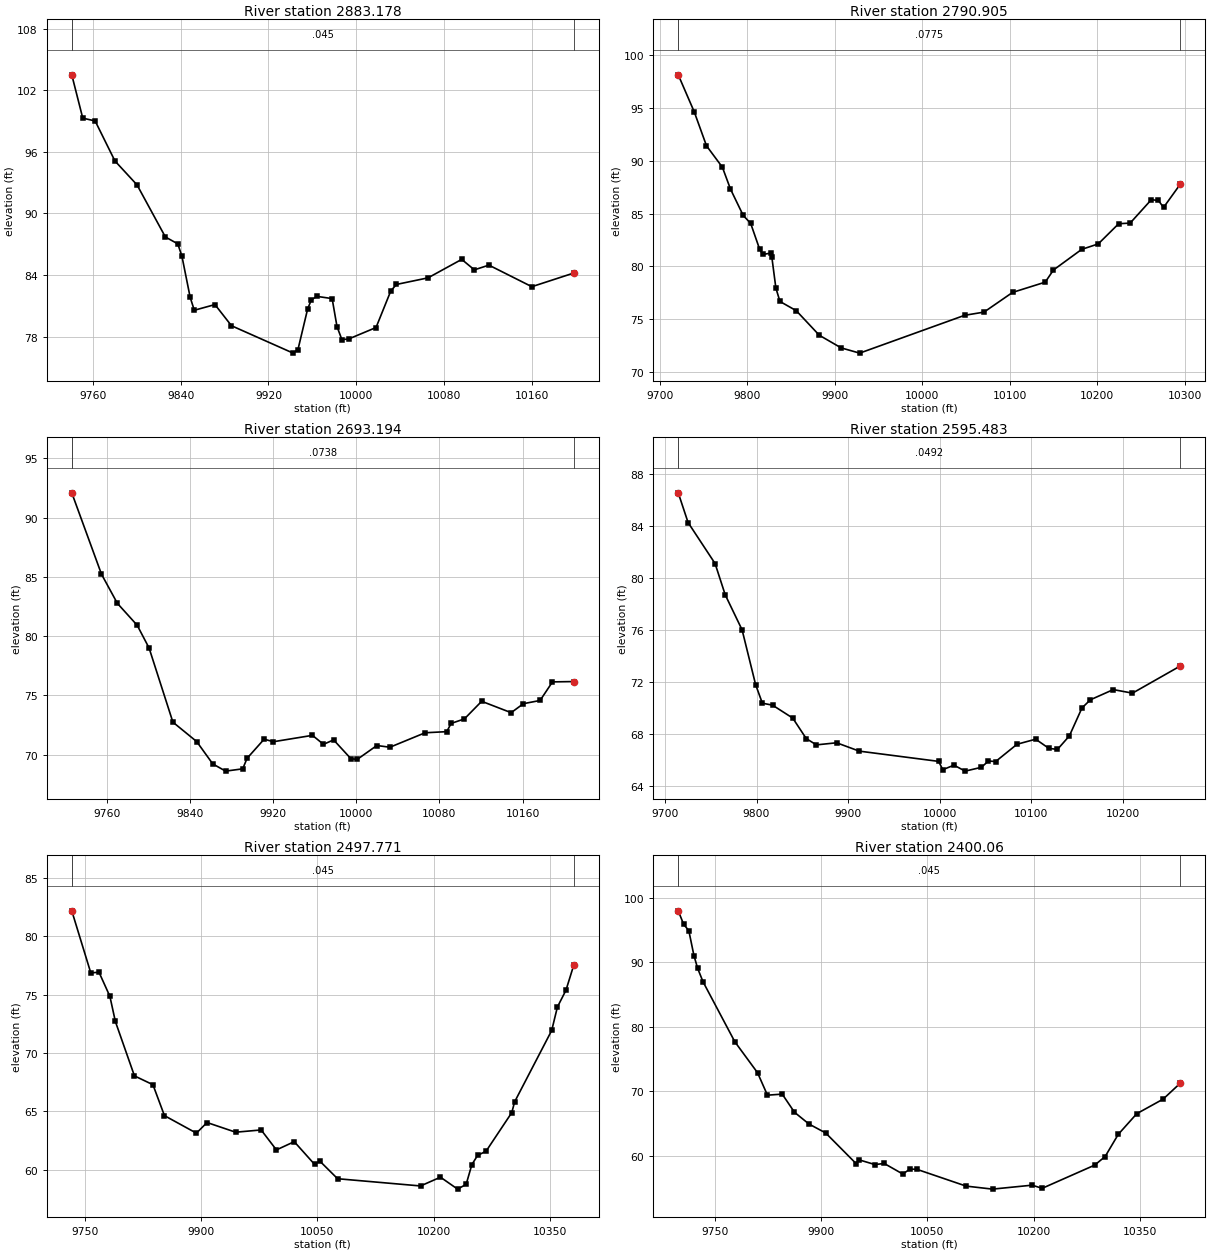
Type RM Length L Ch R = 1 ,2883.178,92.273000,92.273000,92.273000
XS GIS Cut Line= 6
1289372.82170784629237.749276191 1289501.2785438629165.734185517
1289543.72608417629136.0630884621289607.67922205629070.829181597
1289629.94165349629052.4647176561289749.74584273628984.610501036
#Sta/Elev= 30
9740.922 103.4949750.91899.277579762.20299.002179780.21595.107959800.34292.77629
9826.14387.705259837.42687.035649841.18885.84458 9848.71 81.82999852.47180.56849
9871.27781.122989886.32279.063249942.46776.395129946.86576.746219955.66180.69747
9959.00681.569899963.933 81.92399977.96581.705469982.39478.983399986.82277.71609
9993.00577.7731110017.9478.8885910031.3582.4455610036.4983.0825710065.2883.72494
10095.9585.5237410107.4584.5049110120.7184.9637510159.7982.8642210198.0384.19656
#Mann= 3 , 0 , 0
9740.922   0.045       09740.922   0.045       010198.03   0.045       0
#XS Ineff= 2 , 0
       0 9966.97        10025.81       0
Bank Sta=9740.922,10198.03
Exp/Cntr=0.3,0.1

Type RM Length L Ch R = 1 ,2790.905,97.711300,97.711300,97.711300
XS GIS Cut Line= 2
1289434.28004119629365.9610817581289837.92587453628957.974970639
#Sta/Elev= 30
 9720.9698.14361 9739.2794.632889753.26491.41921 9771.43 89.38969780.66187.32263
9795.24884.819089803.73784.074599813.90781.646119817.58281.124419826.81381.25595
9827.90180.910039832.56677.944789837.23176.67254 9855.89 75.79819882.19573.47284
9907.203 72.27399928.34771.7780310048.3475.3612210070.4775.6634510103.1377.53001
10140.4478.5019610149.8879.6543110182.1881.6091310201.0982.1250410224.41 84.0371
10237.5684.0978910261.7386.3138110269.8786.2377510275.7285.5792710294.8887.78551
#Mann= 3 , 0 , 0
 9720.96  0.0775       0 9720.96  0.0775       010294.88  0.0775       0
#XS Ineff= 2 , 0
       09958.775        10057.76       0
Bank Sta=9720.96,10294.88
Exp/Cntr=0.3,0.1

Type RM Length L Ch R = 1 ,2693.194,97.711400,97.711400,97.711400
XS GIS Cut Line= 6
1289471.78004119629406.1520539821289586.00053614629338.328748167
1289628.23594192629306.2983780211289658.29249635 629276.59135583
 1289729.5900965629190.6317032131289844.68425074629105.805695042
#Sta/Elev= 30
9726.32692.090479754.92585.219489770.18882.762379789.266   80.919800.71378.98889
9823.607 72.7341  9846.571.095249861.96969.208029874.32168.599869890.79268.79401
9894.90969.67426 9911.3871.296889920.34371.081959957.86271.620289968.47770.86117
9978.20671.237719994.90169.64412   10001 69.593910019.8170.7617710032.3970.61718
10066.2271.8374610087.0471.9322110091.2872.6285810103.9973.0040810120.6574.49397
   1014973.53317 10160.874.2924310176.8474.5639210188.7776.1317710209.3276.16008
#Mann= 3 , 0 , 0
9726.326  0.0738       09726.326  0.0738       010209.32  0.0738       0
#XS Ineff= 2 , 0
       0 9973.02        10061.34       0
Bank Sta=9726.326,10209.32
Exp/Cntr=0.3,0.1

Type RM Length L Ch R = 1 ,2595.483,97.711300,97.711300,97.711300
XS GIS Cut Line= 6
1289506.50226343 629442.610387311289682.38144898629352.579980642
1289755.77470455629306.1324386451289757.48969039 629305.10344708
1289839.06625232 629252.995454491289954.41893008629135.318720654
#Sta/Elev= 30
9714.56186.579529725.29384.289919754.77981.123879765.83678.713989784.26476.00822
9799.00771.787159806.37870.352029817.51370.20012 9839.5569.202949854.29267.62219
9865.34967.136729887.46467.298389912.14466.654429998.74165.8641810003.3565.22389
10015.5465.5712810027.7365.1118810045.4265.4057810053.2165.8946510060.9965.85067
10084.3567.1848810104.7167.57585 10119.166.8690210128.4866.7865810141.4667.82562
10155.24 69.985810164.4370.6146110189.4171.4009410210.3771.1276710262.5873.22311
#Mann= 3 , 0 , 0
9714.561  0.0492       09714.561  0.0492       010262.58  0.0492       0
#XS Ineff= 2 , 0
       0 9971.39        10049.05       0
Bank Sta=9714.561,10262.58
Exp/Cntr=0.3,0.1

Type RM Length L Ch R = 1 ,2497.771,97.711300,97.711300,97.711300
XS GIS Cut Line= 6
1289532.54393008 629459.971498431289708.51774883 629396.89478077
 1289753.5224092629390.7596710181289873.94499144629390.129997879
 1289937.8389079629374.5561381431290141.91893008 629270.73538731
#Sta/Elev= 30
9732.98482.16773 9757.5476.849419768.10376.913059782.18774.844219789.22972.69603
9813.87568.033869837.74567.278279852.60664.630329893.86663.129249907.54464.04056
9944.52163.210679977.42563.404329997.12961.6944710020.1462.4003510046.44 60.4507
10053.0360.7445810076.0859.2271510183.1258.6084710208.89 59.358810230.9858.33635
10242.0258.7471610249.3860.4348410256.7461.2200610267.7861.5885410300.91 64.8885
10304.5965.8115810352.4571.9252810359.8173.9337510370.8575.3694410381.0277.54387
#Mann= 3 , 0 , 0
9732.984   0.045       09732.984   0.045       010381.02   0.045       0
#XS Ineff= 2 , 0
       09972.319        10022.38       0
Bank Sta=9732.984,10381.02
Exp/Cntr=0.3,0.1

Type RM Length L Ch R = 1 , 2400.06,97.711400,97.711400,97.711400
XS GIS Cut Line= 6
 1289492.7582258629571.580816999 1289674.3598235629500.299119875
1289845.69585726629487.0288122151289918.61922878629471.534878522
1289995.07667068629442.5285404321290157.54393008629355.804831743
#Sta/Elev= 30
9698.52197.940689706.16295.845519713.435 94.87239720.70990.989489725.95889.00999
9733.56186.92977 9778.3577.648819810.41272.845019824.37869.36689 9845.2369.53053
9862.536 66.71669882.94464.896959906.53463.510959949.721   58.739953.024 59.3648
9976.00758.611749989.13458.7814510015.3857.1415710025.2357.9095310035.0857.87797
10104.6255.2739610141.9154.8044410197.7555.4171910211.9954.9301910285.8958.51737
10300.7759.8507510319.3663.3024310345.3966.4962910382.5868.7533410406.8571.22799
#Mann= 3 , 0 , 0
9698.521   0.045       09698.521   0.045       010406.85   0.045       0
#XS Ineff= 2 , 0
       09965.458        10040.12       0
Bank Sta=9698.521,10406.85
Exp/Cntr=0.3,0.1

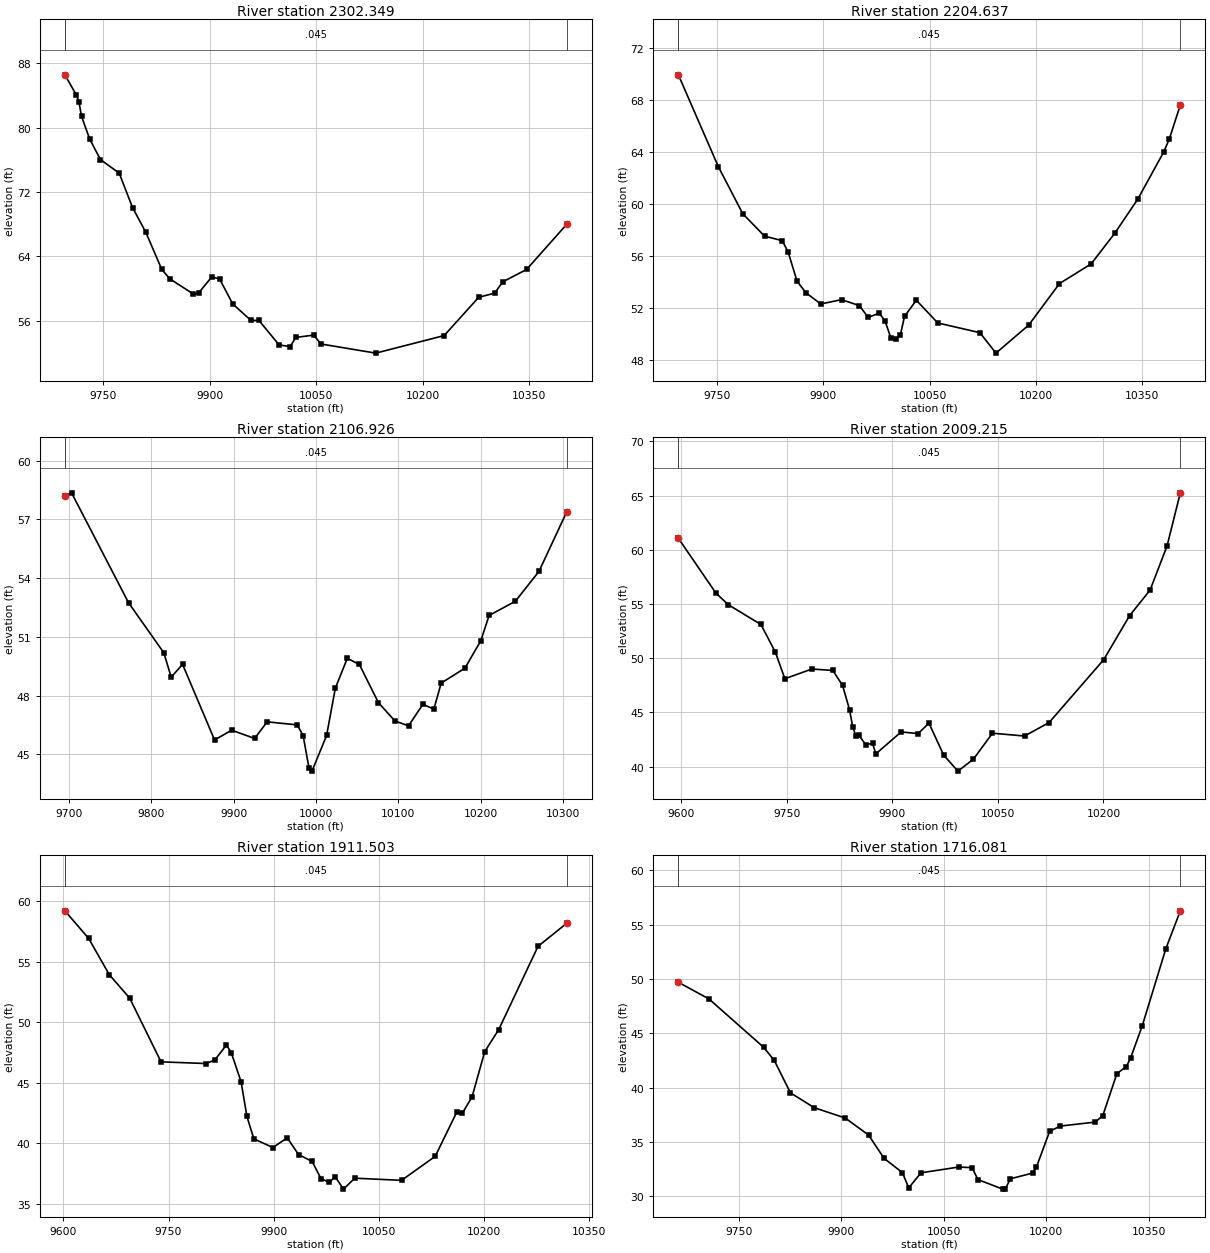
Type RM Length L Ch R = 1 ,2302.349,97.711300,97.711300,97.711300
XS GIS Cut Line= 6
1289538.36843526629725.2222396731289601.57362881629688.745577469
1289677.12918526629647.6661950651289836.47424293629565.917290851
1289959.12576157629507.6564691661290162.75226343 629395.73538731
#Sta/Elev= 30
9696.42486.543929712.43184.057869716.11883.208539719.906  81.3679731.269 78.5736
9746.42176.021849772.88774.321799791.55970.057149810.23166.993949832.63862.38425
9843.84161.212459877.16759.30759 9884.5459.438439902.97361.430749914.03261.19661
9932.46458.092089958.26956.024629969.32956.03961 9997.8552.9874910013.5952.77883
10020.9753.9163910046.6154.2100110056.5353.1055710133.7851.96918   10230 54.1501
10278.6758.9082310301.1359.4229610312.3660.8200110346.05 62.368510402.6467.99098
#Mann= 3 , 0 , 0
9696.424   0.045       09696.424   0.045       010402.64   0.045       0
#XS Ineff= 2 , 0
       09958.089        10048.02       0
Bank Sta=9696.424,10402.64
Exp/Cntr=0.3,0.1

Type RM Length L Ch R = 1 ,2204.637,97.711300,97.711300,97.711300
XS GIS Cut Line= 6
1289611.72660267 629850.070548491289711.98033088629775.861821994
1289828.82058546629683.4416898641289876.55591485629651.694222018
1289998.46904084629548.2351751181290174.90504116629420.040942863
#Sta/Elev= 30
9695.09769.929049751.58762.853139786.04559.234189816.89757.503029841.92357.15652
9850.28956.261179862.83954.025079875.38853.139489896.30452.280629925.58652.61216
9950.68452.157789963.23451.248549978.882 51.5736 9987.2150.956549995.09549.68915
10002.7749.5957210008.6549.8838210014.5451.3213810031.2652.57034 10061.550.81987
10121.05 50.068610143.7348.4950610189.9550.6538610233.4653.8514110278.12  55.365
10311.6157.7310710344.0660.3548210380.5663.9727310388.6765.0001410404.1567.60036
#Mann= 3 , 0 , 0
9695.097   0.045       09695.097   0.045       010404.15   0.045       0
#XS Ineff= 2 , 0
       09973.472        10033.87       0
Bank Sta=9695.097,10404.15
Exp/Cntr=0.3,0.1

Type RM Length L Ch R = 1 ,2106.926,97.711400,97.711400,97.711400
XS GIS Cut Line= 6
 1289742.8413426629952.0232490211289883.64214672629812.243911544
1289956.93573203629669.4455170961289992.06807329629618.847984997
1290054.83437738629556.5363714121290133.87252889629495.709529734
#Sta/Elev= 30
9695.12758.212729703.24658.363289772.45852.74359  9815.350.185099824.25948.93734
9838.06349.595329876.91745.72875 9897.7746.227579925.61245.804039940.79246.65475
9977.33446.498129984.506 45.95479991.67844.284789995.26444.1343110013.0245.95688
10023.6648.3764410038.1749.9040310052.8649.5870410076.0447.6315110095.9546.70222
10112.5246.44867   1013047.5501610143.3347.3046610152.2248.6349710181.0349.39712
10200.3950.8045510210.4452.0950710242.2252.8160510270.9354.3416910304.8757.40203
#Mann= 3 , 0 , 0
9695.127   0.045       09695.127   0.045       010304.87   0.045       0
#XS Ineff= 2 , 0
       09968.785        10032.96       0
Bank Sta=9695.127,10304.87
Exp/Cntr=0.3,0.1

Type RM Length L Ch R = 1 ,2009.215,97.711300,97.711300,97.711300
XS GIS Cut Line= 6
1289737.40504119630038.0964984151289939.99235484629864.031150356
1290012.09367803629780.1293845031290049.44595987629714.288077191
1290099.85493529629655.2953694021290238.84489465 629538.25923118
#Sta/Elev= 30
9595.93461.059399649.30956.004579666.954 54.93049713.26153.110779733.84250.54742
9747.26648.105699785.59749.000689815.32848.875029829.33647.486889839.14945.25269
 9843.76 43.65359848.014 42.85959852.68442.874389862.022  42.0399871.81542.13808
9876.64441.184229912.48943.199299936.64143.046559952.01744.014429972.88141.06668
9993.17939.5857810015.1640.6849810042.2743.0836910087.8542.8221210122.7744.06634
10200.3949.8676910237.19 53.931210266.2256.2813610290.3460.35149 10309.265.25265
#Mann= 3 , 0 , 0
9595.934   0.045       09595.934   0.045       0 10309.2   0.045       0
#XS Ineff= 2 , 0
       0 9937.22         10038.8       0
Bank Sta=9595.934,10309.2
Exp/Cntr=0.3,0.1

Type RM Length L Ch R = 1 ,1911.503,195.422700,195.422700,195.422700
XS GIS Cut Line= 6
1289761.71059668630078.0270539671289963.26557505 629918.44525969
1290011.86663279629881.6964268831290090.79251251629826.010815173
1290209.07389152629747.9980300371290340.43116096629655.945161477
#Sta/Elev= 30
9602.01859.204399636.015   56.929665.30753.93469  9694.651.979939739.29846.71965
9803.402 46.58139815.95646.864789832.69448.115179839.71947.454289853.61845.06875
9861.93842.206059871.79240.357249898.95639.636119919.52240.440229935.58239.05985
9954.98438.484919967.67937.070379979.71536.750029987.73937.236489999.78836.19819
 10015.937.1039810082.7336.9235610130.7938.9091710161.3942.54757 10169.442.46064
10183.3643.8260110201.45 47.560710221.4849.3920110277.5756.2685510318.7258.18665
#Mann= 3 , 0 , 0
9602.018   0.045       09602.018   0.045       010318.72   0.045       0
#XS Ineff= 2 , 0
       0                10035.55       0
Bank Sta=9602.018,10318.72
Exp/Cntr=0.3,0.1

Type RM Length L Ch R = 1 ,1716.081,195.422600,195.422600,195.422600
XS GIS Cut Line= 6
1289876.74258775630190.939533725 1290027.8009603630086.725782365
1290185.62274614629993.2436773931290309.91054851629925.923999414
1290375.05543014629885.2941485641290497.82170787629800.249276206
#Sta/Elev= 30
9661.64949.704069706.37148.170059786.26743.729379802.00442.508719825.60939.52629
9860.41838.155379905.84237.203549939.90935.639769962.62133.49438 9989.5332.17529
9998.72930.7690910016.7432.1588410071.8332.68904 10091.432.6368510099.9831.53754
10136.2230.6563910139.9930.6602110147.4931.6068810180.0332.1354110185.6332.68766
10204.9635.9816910220.4336.4629410271.4636.82766 10282.737.4211110303.3941.29462
10317.2741.9469510323.3542.7263710340.31 45.663310374.8852.7731610396.1656.28076
#Mann= 3 , 0 , 0
9661.649   0.045       09661.649   0.045       010396.16   0.045       0
#XS Ineff= 2 , 0
       09968.974        10044.64       0
Bank Sta=9661.649,10396.16
Exp/Cntr=0.3,0.1

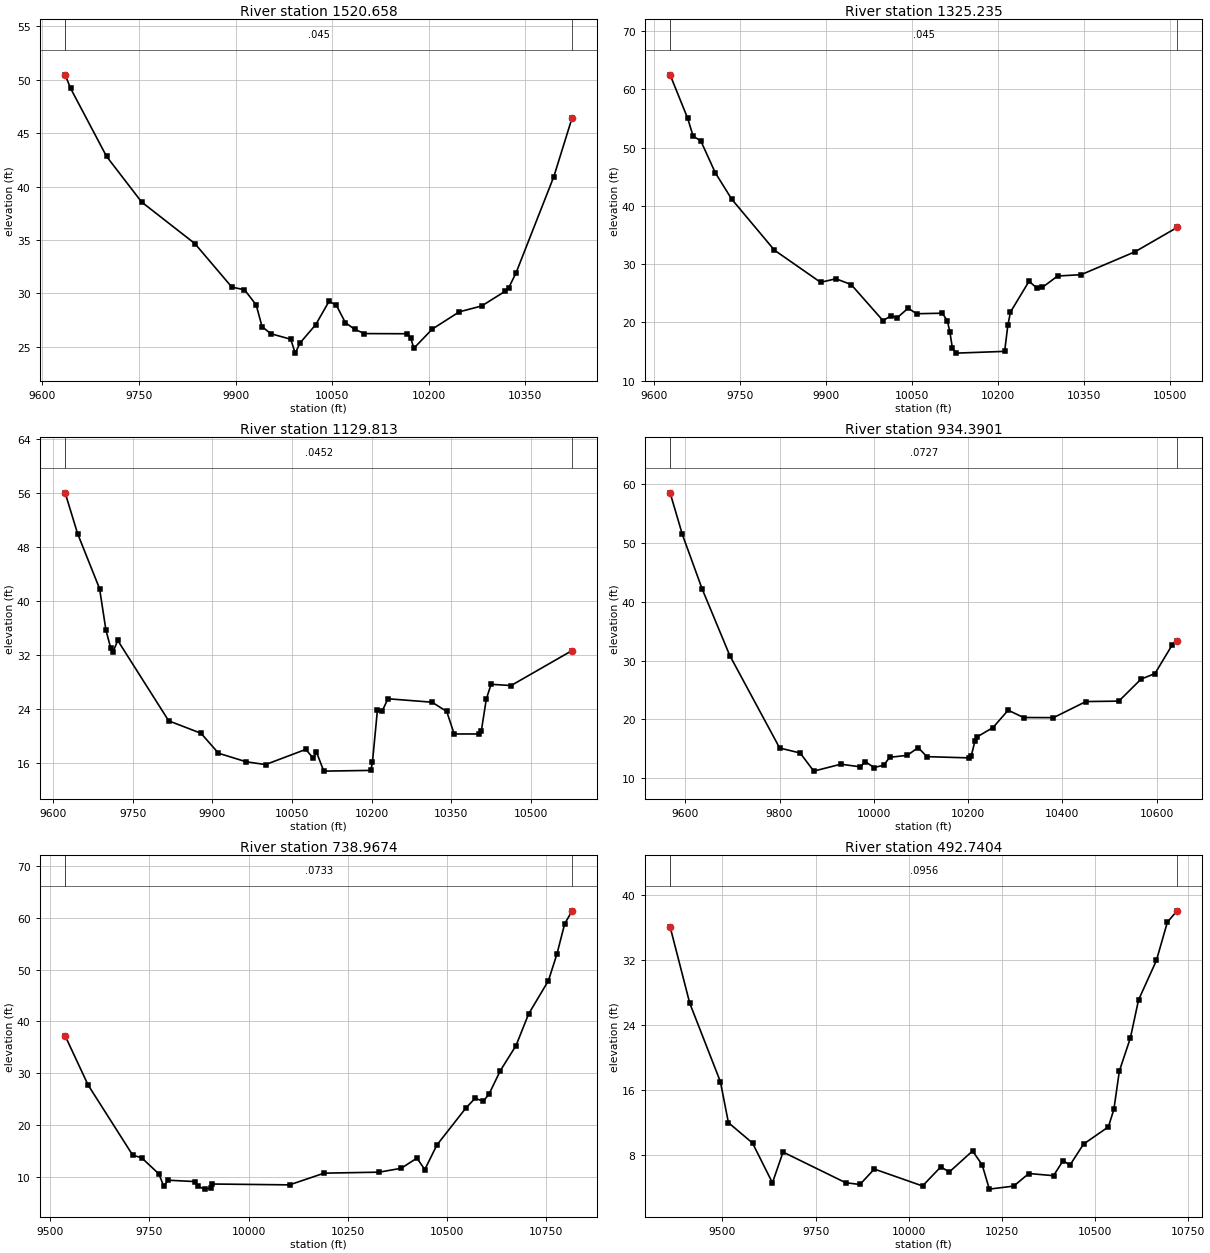
Type RM Length L Ch R = 1 ,1520.658,195.422700,195.422700,195.422700
XS GIS Cut Line= 6
1290002.95358419630414.9838837981290214.22172487630231.231329039
1290252.61954457630190.6398720441290287.12087047630141.666372672
1290321.55363742630107.6680492161290588.09948564629892.263165087
#Sta/Elev= 30
 9635.49 50.46339643.998 49.19169699.75942.823289754.24638.546879836.81334.65772
9894.331 30.57219913.90830.333089932.09728.906129941.12926.879049954.67826.21477
9985.70425.693859992.58724.3935810000.47 25.367510024.5527.06665 10045.129.24234
10056.4428.8935510070.4527.2520910084.8926.6285310100.1726.22437 10166.426.20868
10171.8425.8379910176.8224.8485210205.3926.6449110247.3428.2613510282.1428.81159
10319.0130.2071210324.2830.5390710335.41 31.905610394.1340.9316810422.4846.43715
#Mann= 3 , 0 , 0
 9635.49   0.045       0 9635.49   0.045       010422.48   0.045       0
#XS Ineff= 2 , 0
       09953.602        10042.37       0
Bank Sta=9635.49,10422.48
Exp/Cntr=0.3,0.1

Type RM Length L Ch R = 1 ,1325.235,195.422700,195.422700,195.422700
XS GIS Cut Line= 6
1290146.14189756630571.3240058271290218.07522944630504.594598025
1290291.12859377630431.4952320161290415.45515236630295.635721251
1290483.18890846630218.5915642081290757.80434671629934.363859534
#Sta/Elev= 30
9628.27562.463829658.81755.022649668.46551.940279681.74951.138629707.05845.65943
9735.63241.138469810.04732.39475 9890.5526.880029917.16127.490729943.77326.49923
9999.18720.3191210013.2621.1283410023.9620.8031610043.0422.4388910057.9521.49266
10102.5921.5820910111.3320.29402 10115.718.4322910120.1915.6022410127.0914.73753
10211.2615.0390210216.7919.4839210221.4121.7804710253.7127.0555210267.24 25.9078
10276.9926.0140210303.6427.9639410344.5228.1890610438.2832.1113710511.7436.28365
#Mann= 3 , 0 , 0
9628.275   0.045       09628.275   0.045       010511.74   0.045       0
#XS Ineff= 2 , 0
       0 9942.75        10039.69       0
Bank Sta=9628.275,10511.74
Exp/Cntr=0.3,0.1

Type RM Length L Ch R = 1 ,1129.813,195.422600,195.422600,195.422600
XS GIS Cut Line= 6
1290289.41060692 630689.451901511290365.72659308630619.636611506
1290427.76987982630559.6378473491290558.20784619630426.742534041
1290689.14212751630291.7073790581290966.13768005 630016.82913731
#Sta/Elev= 30
9623.046 56.02159646.52749.964319687.86941.800879699.88635.627879708.77933.02024
9713.22632.470489722.11934.117579817.98122.197659878.86920.348419911.65517.39567
 9963.4316.13289 10000.215.7060510076.0617.96273 10090.216.6313310096.1717.55338
10109.8814.7375310198.3714.8447910201.5716.1001310210.8923.8056410220.22 23.7161
10230.6825.4714210313.8424.9601310341.36 23.583310355.3320.2493410401.6920.24934
10406.3220.6342110415.8625.4309310424.8127.6203510462.4227.4292210577.3332.62506
#Mann= 3 , 0 , 0
9623.046  0.0452       09623.046  0.0452       010577.33  0.0452       0
#XS Ineff= 2 , 0
       09960.773        10057.09       0
Bank Sta=9623.046,10577.33
Exp/Cntr=0.3,0.1

Type RM Length L Ch R = 1 ,934.3901,195.422700,195.422700,195.422700
XS GIS Cut Line= 6
 1290362.0253557630860.2215630861290464.50554883630778.362350836
1290562.33557492630691.837242067 1290702.5520632630557.542243198
1290868.68192533630391.4794522671291144.08906898630123.165942878
#Sta/Elev= 30
9567.95558.49968 9593.7751.46115 9635.7642.201319694.54630.863149800.32115.15377
9843.78814.307369872.65211.22859 9930.21 12.40759971.14611.955799981.59912.84571
10000.5911.8408110020.9612.2315810033.7613.5749310070.8913.9083610094.09 15.2255
10112.6513.68649 10201.813.4774810206.4413.7388110214.75 16.399410219.3917.05892
10252.8318.6294910284.96 21.578710317.6120.3341110381.1520.3123710449.8623.04456
10519.7723.1194410566.7926.8529510596.4327.8017210632.61 32.626210643.2733.36494
#Mann= 3 , 0 , 0
9567.955  0.0727       09567.955  0.0727       010643.27  0.0727       0
#XS Ineff= 2 , 0
       09963.523        10042.14       0
Bank Sta=9567.955,10643.27
Exp/Cntr=0.3,0.1

Type RM Length L Ch R = 1 ,738.9674,246.227000,246.227000,246.227000
XS GIS Cut Line= 2
1290449.03698561630960.9046581391291506.32865226630244.758824825
#Sta/Elev= 30
9537.62837.230799595.58727.736789707.72714.242449730.31613.729999773.904 10.6084
9785.792 8.28996 9797.68 9.404229865.044 9.145249871.5338.259417 9888.827.688694
 9904.67 7.919149908.6338.673692 10102.88.51016810189.9810.7661810328.6710.95833
10384.1411.7030210423.7713.6697810443.58 11.455210474.1116.1998310546.6123.27611
10570.3925.2063110591.1124.6024710606.0526.1130310633.7930.5128910673.41 35.3603
10705.1241.4566610754.92 47.851210776.4452.9995210795.8758.8094810814.6361.32331
#Mann= 3 , 0 , 0
9537.628  0.0733       09537.628  0.0733       010814.63  0.0733       0
#XS Ineff= 2 , 0
       0    9924        10057.82       0
Bank Sta=9537.628,10814.63
Exp/Cntr=0.3,0.1

Type RM Length L Ch R = 1 ,492.7404,443.208600,443.208600,443.208600
XS GIS Cut Line= 6
1290436.23316616631103.5912901011290718.30431315630979.127513677
1290977.90063757630881.5569648441291056.45134082630830.636429891
1291115.10316548630797.2732801441291661.92761064630518.521845654
#Sta/Elev= 30
9359.39736.102319412.08526.688739494.31817.013659515.88911.961429580.5879.444026
9634.0514.5378019662.5658.3299729830.6464.5518499868.9494.3340879907.5286.237832
10036.924.15035910086.066.50990310108.655.86579710171.268.46921810197.036.754218
10216.223.76154310281.734.13688210322.245.68556910388.52 5.42007 10414.37.269871
10432.716.72432410469.069.31140210535.8211.4384710550.5513.5988710565.2918.33096
10594.7522.3872610616.84 27.103910664.7131.9552510694.1736.6869310720.1838.07736
#Mann= 3 , 0 , 0
9359.397  0.0956       09359.397  0.0956       010720.18  0.0956       0
#XS Ineff= 2 , 0
       09896.057        10085.42       0
Bank Sta=9359.397,10720.18
Exp/Cntr=0.3,0.1

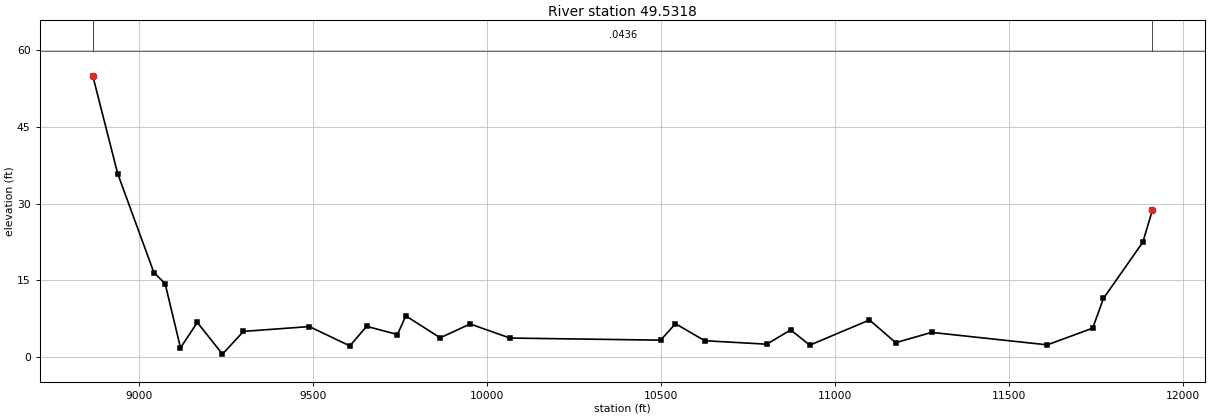
Type RM Length L Ch R = 1 , 49.5318,0.000000,0.000000,0.000000
XS GIS Cut Line= 5
1290051.90156898631914.0296581391290784.97233832631395.079300582
1291029.47680041631253.1500285121291453.08791155631037.872250751
1292780.63420784 630635.38382481
#Sta/Elev= 30
    886855.004268939.48135.873269043.55616.49535 9075.7614.34962 9119.93 1.77007
9168.1676.7441069240.522 0.542199300.8184.9927319489.7445.9340599606.3162.155616
9654.5525.9788219742.9864.3831319767.0518.0259949865.6833.7402079951.8456.438104
10066.213.68802110498.963.27578110541.416.500976 10625.53.16703410803.77  2.4857
10872.345.28200510927.192.29636111098.617.22623311174.032.78242211276.884.794377
11609.422.355916 11739.75.62520411770.5611.4406111883.6922.4508711911.2728.74314
#Mann= 3 , 0 , 0
    8868  0.0436       0    8868  0.0436       011911.27  0.0436       0
#XS Ineff= 2 , 0
       09945.613        10057.84       0
Bank Sta=8868,11911.27
Exp/Cntr=0.3,0.1